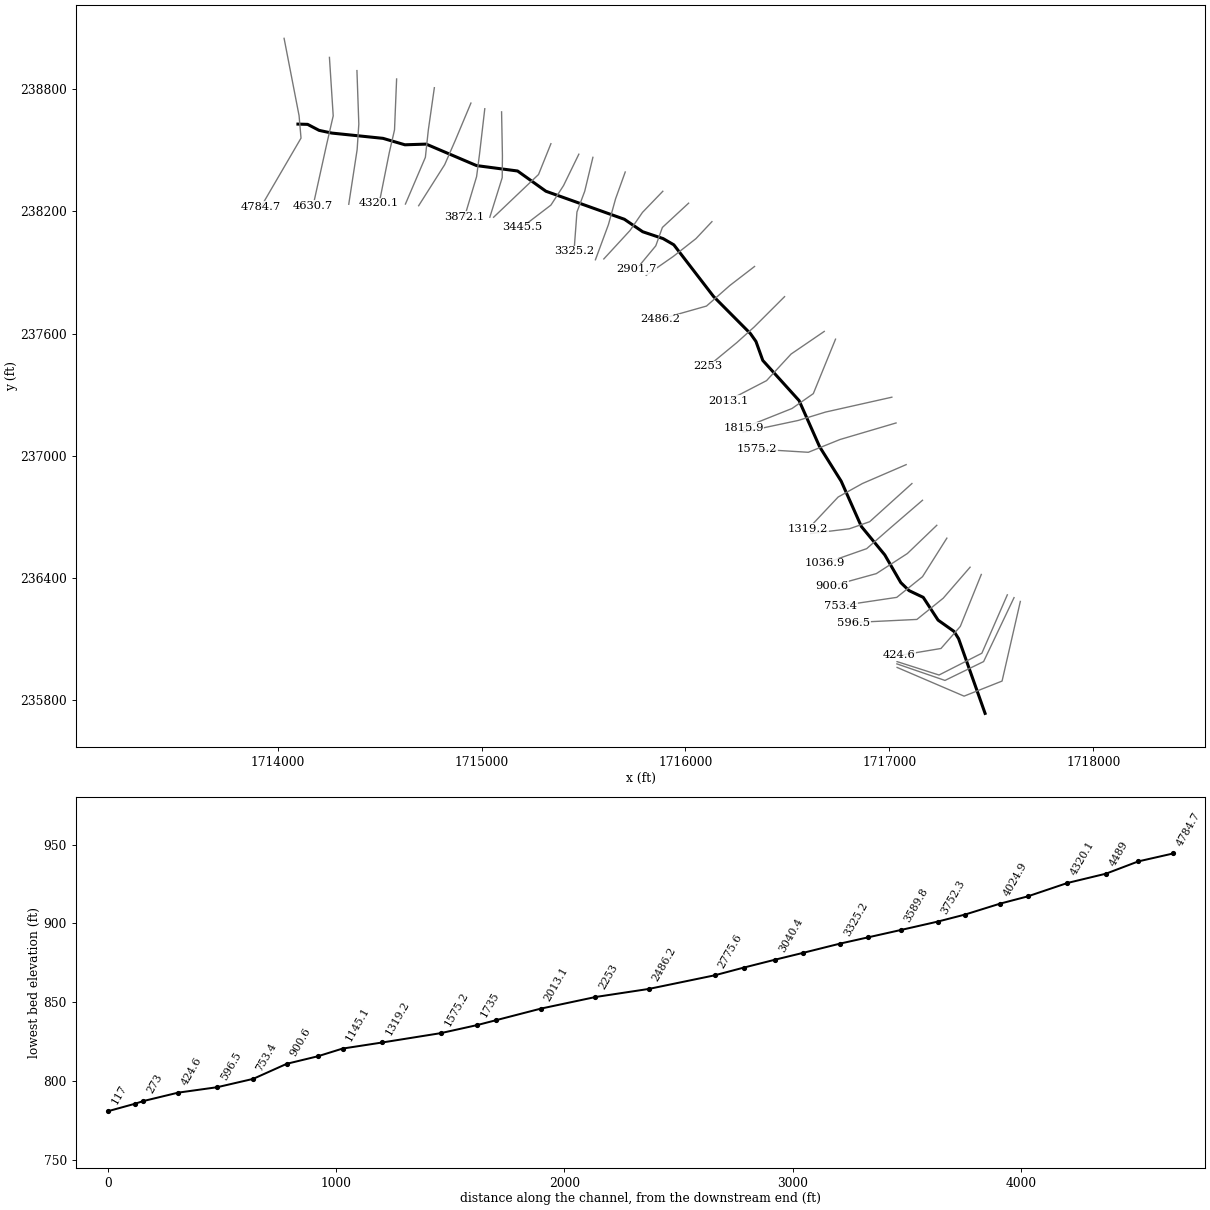
--- cnbrkbrnch.prj (project) ---

Proj Title=cnbrkbrnch
Current Plan=p01
Default Exp/Contr=0,0
English Units
Geom File=g01
Flow File=f01
Plan File=p01
BEGIN DESCRIPTION:
END DESCRIPTION:
DSS Export Rating Curves= 0
DSS Export Rating Curve Sorted= 0
DSS Export Volume Flow Curves= 0
DXF OffsetX= 0
DXF OffsetY= 0
DXF ScaleX= 0
DXF ScaleY= 0

--- cnbrkbrnch.p01 (plan) ---

Plan Title=Floodplain
Program Version=4.00
Geom File=g01
Flow File=f01
K Sum by GR=0
Std Step Tol=0.01
Critical Tol=0.01
Num of Std Step Trials=20
Max Error Tol=0.3
Flow Tol Ratio=0.001
Split Flow NTrial=30
Split Flow Tol=0.02
Split Flow Ratio=0.02
Log Output Level=0
Friction Slope Method=1
Unsteady Friction Slope Method=2
Unsteady Bridges Friction Slope Method=1
Global Log Level=0
CheckData=False
Run HTab=0
Run UNet=0
Run PostProcess=0
UNET Theta=0
UNET Theta Warmup=0
UNET ZTol=0
UNET ZSATol=0
UNET MxIter=0
UNET MaxInSteps=0
UNET DtIC=0
UNET DtMin=0
UNET MaxCRTS=0
UNET WFStab=0
UNET SFStab=0
UNET WFX=0
UNET SFX=0
UNET DSS MLevel=0
UNET DZMax Abort=0
UNET Convert EG Bridges=0
UNET Use Existing IB Tables=0
UNET Froude Limit=0
UNET Froude Power=0
Write IC File=0
Echo Input=False
Echo Output=False
Write Detailed=0

--- cnbrkbrnch.f01 (steady flow) ---

Flow Title=NFF Regression Equation
Program Version=4.00
Number of Profiles= 1
Profile Names=P100yr
River Rch & RM=cnbrkbrnch,Main            ,4784.7
     397
River Rch & RM=cnbrkbrnch,Main            ,3872.1
     407
River Rch & RM=cnbrkbrnch,Main            ,2486.2
     452
River Rch & RM=cnbrkbrnch,Main            ,273
     496
Boundary for River Rch & Prof#=cnbrkbrnch,Main            , 1
Up Type= 0
Dn Type= 3
Dn Slope=0.016
DSS Import GetInterval= 0
DSS Import GetPeak= 0
DSS Import FillOption= 0

--- cnbrkbrnch.g01 (geometry) ---

Geom Title=USGS 10m DEM
Program Version=4.00

River Reach=cnbrkbrnch      ,Main
Reach XY= 30
     1714099.293      238629.178       1714146.7      238627.935
     1714203.061      238598.404     1714265.787      238585.051
     1714516.422      238559.176     1714623.967      238527.513
     1714728.156      238530.862     1714975.174      238425.301
     1715176.492      238398.738     1715315.336      238299.267
     1715700.189      238161.524     1715790.131      238100.182
     1715890.138       238066.52     1715942.707      238035.992
     1716137.761      237781.799     1716318.498       237599.53
     1716345.559      237561.001     1716379.095      237467.654
     1716557.217      237270.151     1716658.034      237043.096
     1716763.716      236873.927     1716862.543      236651.653
      1716977.29      236512.006     1717056.004      236375.628
     1717096.361      236336.425     1717165.995      236303.236
      1717238.68      236191.455      1717317.18      236135.719
     1717339.466      236099.983     1717469.287      235733.066

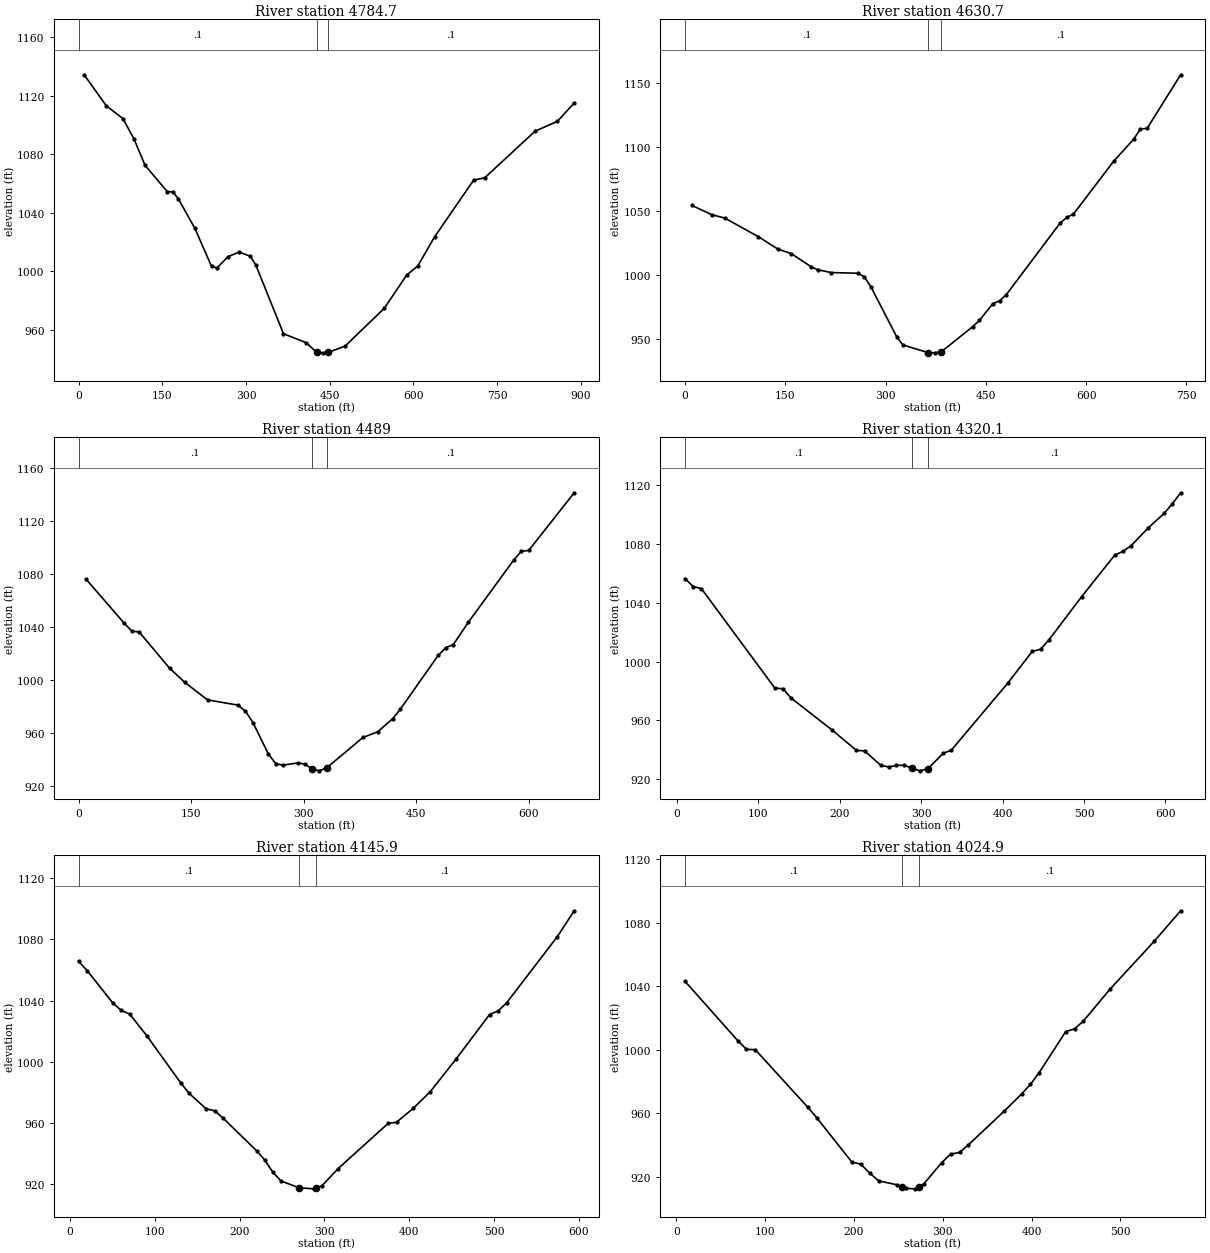
Type RM Length L Ch R = 1 ,4784.7  ,162.1,154,145.9
XS GIS Cut Line= 4
     1714031.363      239050.728     1714104.843      238670.689
       1714114.4      238560.351     1713918.107      238222.929
#Sta/Elev= 30
     9.9 1134.22    49.6 1113.06    79.4 1104.31    99.3 1090.35   119.1 1072.38
   158.8 1054.47   168.7 1054.22   178.7 1049.63   208.4 1029.31   238.2 1003.39
   248.1 1002.41     268 1010.09   287.8 1013.15   307.7 1010.35   317.6 1004.29
   367.2  957.43   407.2  951.38   427.4  944.62   437.4  944.38   447.4   944.7
   477.7  948.99   547.9  974.83   587.9  997.41   607.9 1003.71     638 1023.56
     708 1062.28     728 1063.92   818.1 1095.72   858.2 1102.45   888.2 1114.96
#Mann= 3 , 0 , 0
       0      .1       0   427.4    .045       0   447.4      .1       0
Bank Sta=427.4,447.4
XS Rating Curve= 0 ,0
Exp/Cntr=0.3,0.1

Type RM Length L Ch R = 1 ,4630.7  ,137.7,141.7,145.7
XS GIS Cut Line= 4
     1714253.757      238957.034     1714272.289      238669.776
     1714240.372       238530.78     1714173.448      238227.048
#Sta/Elev= 30
     9.9 1054.29    39.7  1047.1    59.6 1044.37   109.2 1030.01     139 1020.18
   158.8 1016.74   188.6 1006.46   198.5 1004.14   218.4 1001.92   258.1 1001.37
     268  998.71   277.9  990.93   316.4  952.05   325.9  945.46   363.4  939.51
   373.4  939.31   383.4  940.11   430.5   959.8   440.5  964.68   460.6  977.73
   470.6   979.9   480.6  984.69   560.9 1040.32   570.9 1044.86     581 1047.43
   641.2 1088.68   671.3 1105.97   681.3 1113.88   691.3 1114.31   741.5 1156.16
#Mann= 3 , 0 , 0
       0      .1       0   363.4    .045       0   383.4      .1       0
Bank Sta=363.4,383.4
XS Rating Curve= 0 ,0
Exp/Cntr=0.3,0.1

Type RM Length L Ch R = 1 ,4489    ,172.9,168.9,164.9
XS GIS Cut Line= 4
     1714388.634       238892.17     1714397.901      238629.621
     1714389.664       238504.01      1714348.48      238235.284
#Sta/Elev= 30
    10.1 1076.02    60.6 1043.04    70.7 1037.13    80.8  1036.2   121.3 1008.94
   141.5  998.28   171.8  985.06   212.2  981.14   222.3  976.57   232.4  967.91
   252.6  944.53   262.7  936.94   272.4  935.82   291.8  937.45   301.4  936.64
   310.8  933.11   320.8  931.51   330.8  933.84   378.9  956.69   398.7  960.97
   418.8  970.98   428.9  978.14   479.2  1018.6   489.3 1024.48   499.4 1026.81
   519.5 1043.71   579.9 1090.61     590 1097.13     600 1097.93   660.5 1141.39
#Mann= 3 , 0 , 0
       0      .1       0   310.8    .045       0   330.8      .1       0
Bank Sta=310.8,330.8
XS Rating Curve= 0 ,0
Exp/Cntr=0.3,0.1

Type RM Length L Ch R = 1 ,4320.1  ,171.2,174.2,177.2
XS GIS Cut Line= 4
     1714583.229      238850.985     1714572.933      238600.793
     1714547.193      238488.566     1714497.772      238240.432
#Sta/Elev= 30
      10 1056.36      20 1051.03      30 1049.64   120.2  981.93   130.2  981.49
   140.2  975.12   190.3  953.49   220.4  939.54   230.4   939.2   250.4  929.33
     260  928.28   269.6   929.3   279.2  929.42   288.4   927.4   298.4  925.61
   308.4  927.17   327.2  937.66   336.8  939.55     406   985.1   436.4 1006.88
   446.5 1008.33   456.6 1014.55   497.1 1044.19   537.6 1072.37   547.7 1074.94
   557.8 1078.79   578.1 1090.55   598.3  1100.8   608.4 1107.34   618.6 1114.82
#Mann= 3 , 0 , 0
      10      .1       0   288.4    .045       0   308.4      .1       0
#XS Ineff= 2 , 0
       0     279                       0
Permanent Ineff=
       F       F
Bank Sta=288.4,308.4
XS Rating Curve= 0 ,0
Exp/Cntr=0.3,0.1

Type RM Length L Ch R = 1 ,4145.9  ,128.6,121,113.4
XS GIS Cut Line= 4
     1714768.321      238808.105     1714738.699      238599.763
     1714724.284      238465.915     1714626.472      238236.314
#Sta/Elev= 30
      10 1065.55      20 1059.63    50.1 1038.59    60.1  1033.6    70.1 1031.26
    90.2 1017.19   130.3  986.37   140.3  979.47   160.3  969.39   170.4  968.08
   180.4  963.26   220.1   941.9   229.7  935.85   239.3  927.76   248.9  922.17
  270.13  917.76   287.4  917.09  290.25  917.68     297  919.09   316.2  930.34
     375  959.77     385  960.58     405  969.76   424.9  980.57   454.9 1001.58
   494.8 1030.91   504.8 1033.21   514.8 1038.45   574.7 1081.72   594.6 1098.64
#Mann= 3 , 0 , 0
      10      .1       0  270.13    .045       0  290.25      .1       0
Bank Sta=270.13,290.25
XS Rating Curve= 0 ,0
Exp/Cntr=0.3,0.1

Type RM Length L Ch R = 1 ,4024.9  ,145.8,152.8,159.9
XS GIS Cut Line= 4
     1714947.708      238732.581     1714871.517      238550.342
     1714819.007      238429.879     1714691.337      238228.077
#Sta/Elev= 30
     9.9 1043.01    69.1 1005.79      79 1000.27    88.9 1000.06   148.1  963.79
     158  957.28   197.5  929.42   207.6  928.04   217.7  922.38   227.9  917.47
   248.1  915.09  253.74  913.76   258.2  912.88   268.3  912.49  272.91   913.7
   278.4  915.49   298.6  928.86   308.7  934.34   318.8   935.4   328.9  940.24
   368.7  961.16   388.6  972.14   398.6  978.24   408.5  985.65   438.4  1011.5
   448.3 1013.15   458.3 1018.11   488.1 1038.08   537.9 1068.26   567.7 1087.47
#Mann= 3 , 0 , 0
     9.9      .1       0  253.74    .045       0  272.91      .1       0
Bank Sta=253.74,272.91
XS Rating Curve= 0 ,0
Exp/Cntr=0.3,0.1

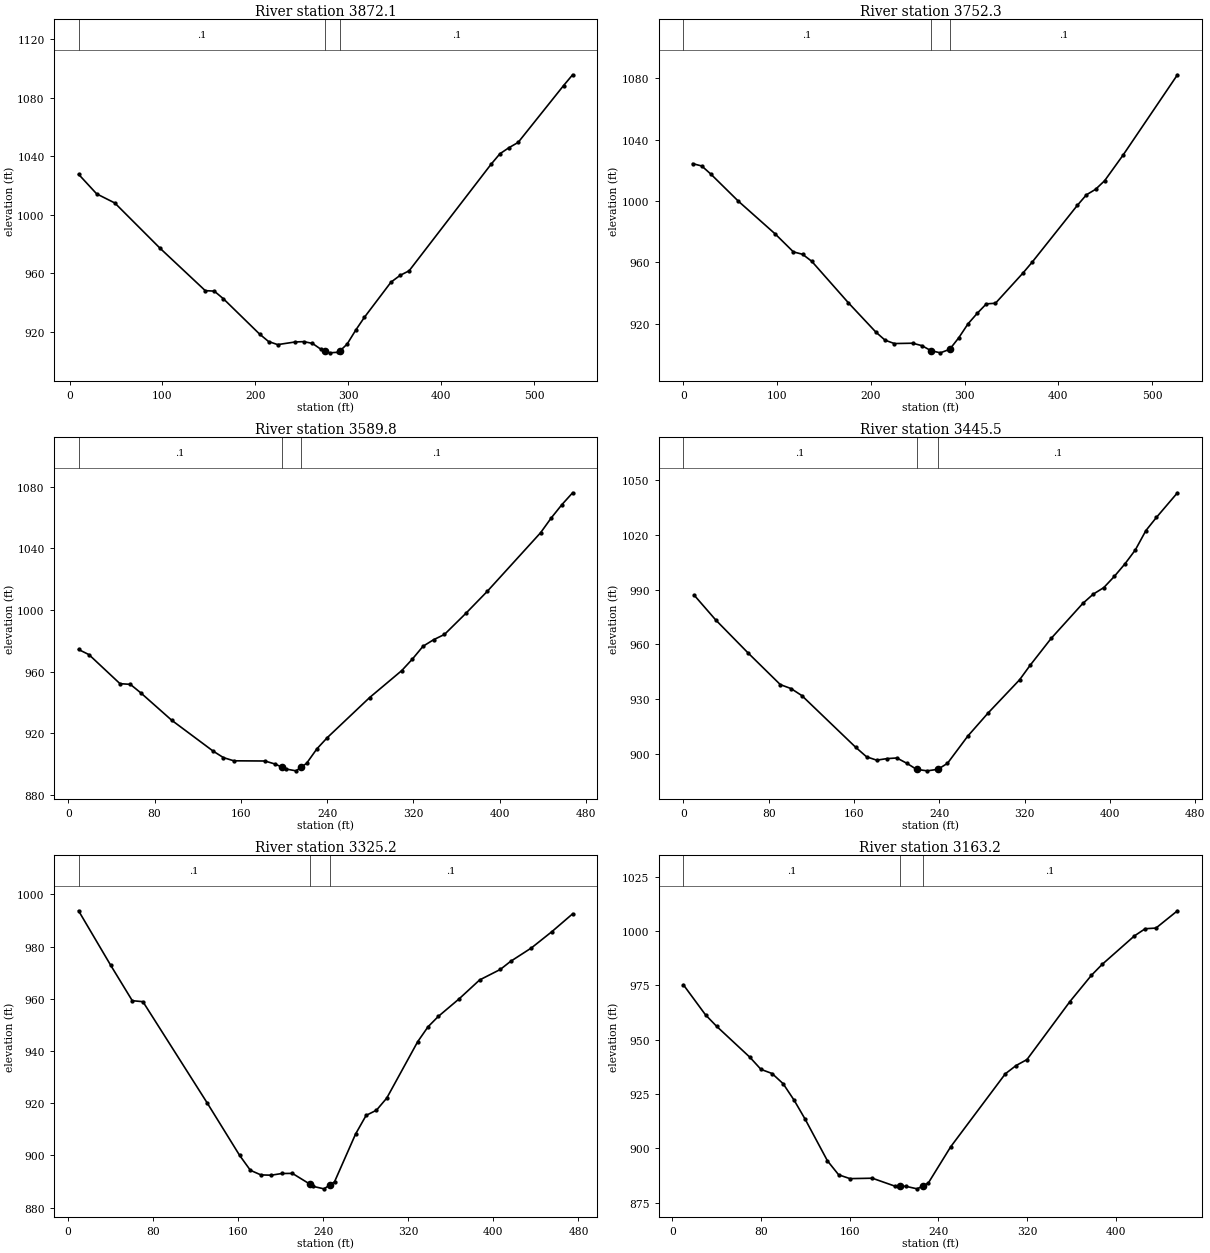
Type RM Length L Ch R = 1 ,3872.1  ,116.7,119.7,122.7
XS GIS Cut Line= 4
     1715015.661      238704.782     1714989.921      238482.389
     1714975.507      238371.192     1714916.819      238174.538
#Sta/Elev= 30
     9.7 1027.64    29.2 1014.23    48.7 1008.01    97.3  977.12     146   948.1
   155.7  947.77   165.5  942.56   204.4  918.44   214.1  913.33   223.9  911.21
   242.6  913.01   251.9  913.25   261.3  912.05   270.6  907.95  275.03  906.79
   279.9  905.59   289.3  906.03  291.22  907.08   298.6  911.55     308  921.24
   317.3  929.95   345.8  953.89   355.6  958.53   365.3  961.65   453.3 1034.34
     463 1041.65   472.8 1045.83   482.6  1049.4   531.5 1088.28   541.2 1095.63
#Mann= 3 , 0 , 0
     9.7      .1       0  275.03    .045       0  291.22      .1       0
Bank Sta=275.03,291.22
XS Rating Curve= 0 ,0
Exp/Cntr=0.3,0.1

Type RM Length L Ch R = 1 ,3752.3  ,182.7,162.5,142.4
XS GIS Cut Line= 4
     1715098.029      238689.338     1715102.148      238474.152
     1715101.118      238366.044     1715040.372      238171.449
#Sta/Elev= 30
     9.8 1024.37    19.6 1022.83    29.3 1017.54    58.7  999.88    97.8  978.66
   117.4  966.87   127.2  965.31     137  960.73   176.1  933.69   205.4  914.62
   215.2  909.37   225.1  907.17   244.7  907.39   254.5   905.8   264.2  902.53
   274.2  901.12   284.2  903.44   293.9  910.98   303.7  919.99   313.5  926.84
   323.3  933.02     333  933.42   362.2  952.99   371.9  959.98   420.4  997.21
   430.1 1004.07   439.8 1007.62   449.5 1013.24     469 1029.77   527.2 1082.24
#Mann= 3 , 0 , 0
       0      .1       0   264.2    .045       0   284.2      .1       0
Bank Sta=264.2,284.2
XS Rating Curve= 0 ,0
Exp/Cntr=0.3,0.1

Type RM Length L Ch R = 1 ,3589.8  ,138.4,144.3,150.3
XS GIS Cut Line= 4
     1715339.985      238532.839     1715279.239      238381.488
     1715216.433      238321.771     1715058.904      238171.449
#Sta/Elev= 30
     9.6  974.47    19.2  971.15      48  952.29    57.6  951.86    67.2  946.38
    95.9  928.59   134.3  908.57   143.9  904.33   153.5  902.27   182.3  902.14
     192  900.12  198.04  898.13   201.6  896.96   211.2  895.76  215.46  897.94
   220.9  900.59   230.5  910.03   240.1  917.28   279.4  943.32   309.1  960.76
     319  968.25   328.9  976.58   338.8  980.86   348.7  984.21   368.5  997.87
   388.3 1012.11   437.8 1050.18   447.7  1059.8   457.6 1068.45   467.5 1076.11
#Mann= 3 , 0 , 0
     9.6      .1       0  198.04    .045       0  215.46      .1       0
Bank Sta=198.04,215.46
XS Rating Curve= 0 ,0
Exp/Cntr=0.3,0.1

Type RM Length L Ch R = 1 ,3445.5  ,114.8,120.3,125.7
XS GIS Cut Line= 4
     1715476.922      238481.359     1715401.761      238326.919
     1715339.985      238231.166      1715198.93      238123.058
#Sta/Elev= 30
    10.1  986.92    30.3   973.4    60.6  955.43    90.9  938.12     101  935.94
   111.1  932.12   161.7  903.87   171.8  898.73   181.3  896.89   190.8  897.73
   200.2  898.09   209.7  895.15   218.7  891.87   228.7  891.07   238.7   891.9
   247.7  895.17   266.7  909.99   285.7  922.56   315.3  940.72   325.2  948.63
   344.9  963.29   374.6  982.39   384.4  987.46   394.3  991.03   404.2  997.15
   414.1 1003.95   423.9 1011.59   433.8 1022.14   443.7 1029.34   463.4 1042.77
#Mann= 3 , 0 , 0
       0      .1       0   218.7    .045       0   238.7      .1       0
Bank Sta=218.7,238.7
XS Rating Curve= 0 ,0
Exp/Cntr=0.3,0.1

Type RM Length L Ch R = 1 ,3325.2  ,159.8,162,164.2
XS GIS Cut Line= 4
     1715545.905      238465.915     1715505.751       238299.12
     1715467.656      238197.189     1715453.241      238003.624
#Sta/Elev= 30
    10.1  993.75    40.4   972.8    60.6  959.29    70.6  958.91   131.2  919.98
   161.5     900   171.6  894.29   181.5  892.52   191.3  892.41   201.2  893.06
   211.1   893.1  227.47     889   230.9  888.09   240.8  887.18   246.1   888.6
   250.7  889.88   270.5  908.19   280.4  915.33   290.1  917.31   299.8  921.96
   328.9  943.59   338.6  949.29   348.3  953.28   367.7  959.95   387.1  967.24
   406.5  971.26   416.2  974.36   435.7  979.49   455.1  985.78   474.5  992.58
#Mann= 3 , 0 , 0
    10.1      .1       0  227.47    .045       0   246.1      .1       0
Bank Sta=227.47,246.1
XS Rating Curve= 0 ,0
Exp/Cntr=0.3,0.1

Type RM Length L Ch R = 1 ,3163.2  ,131.1,122.8,114.5
XS GIS Cut Line= 4
     1715704.464      238393.843     1715657.102      238262.054
     1715622.096      238135.413      1715558.26       237962.44
#Sta/Elev= 30
      10  975.22      30  961.36      40  956.11      70  941.87      80  936.29
      90  934.39     100   929.7     110  922.03     120  913.24     140  894.19
   150.1  887.77   160.3  886.01   180.5   886.2   200.7  882.58  205.65  882.53
   210.8  882.47   220.9  881.31  226.04  882.63     231  883.99   251.2  900.67
   300.5  934.26   310.2  938.06     320   940.8   358.8  967.52   378.2   979.6
   387.9  984.63     417  997.73   426.7 1001.02   436.4 1001.32   455.8 1009.28
#Mann= 3 , 0 , 0
      10      .1       0  205.65    .045       0  226.04      .1       0
Bank Sta=205.65,226.04
XS Rating Curve= 0 ,0
Exp/Cntr=0.3,0.1

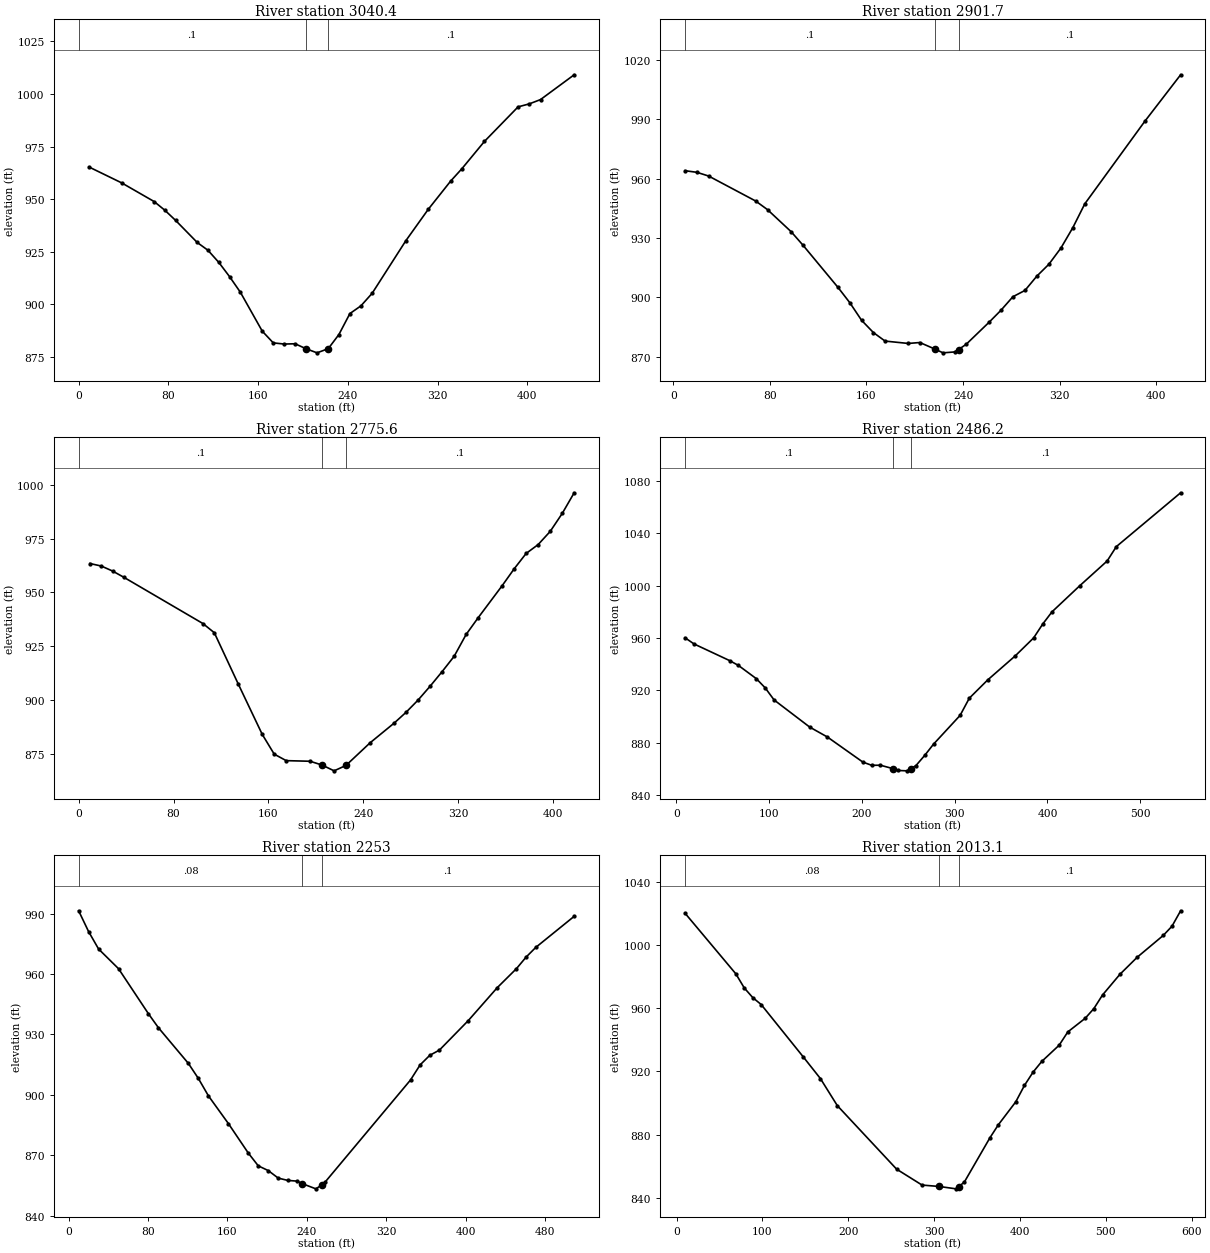
Type RM Length L Ch R = 1 ,3040.4  ,132.2,138.6,145.1
XS GIS Cut Line= 4
     1715888.762       238299.12     1715788.891       238195.13
     1715728.145      238106.584     1715599.445      237966.559
#Sta/Elev= 30
     9.6  965.21    38.4  957.74    67.3  948.88    76.9  944.72    86.5  939.89
   105.7  929.43   115.3  925.71     125  919.92   134.6  913.14   144.2  905.74
   163.7  887.26   173.5   881.7   183.2  881.15     193  881.28   202.5  878.96
   212.5  876.97   222.5  878.96     232  885.68   241.8  895.64   251.6  899.29
   261.6  905.25   291.6  930.22   311.6  945.16   331.6   958.6   341.6  964.47
   361.7  977.45   391.7  993.88   401.7   995.3   411.7  997.34   441.7 1009.13
#Mann= 3 , 0 , 0
       0      .1       0   202.5    .045       0   222.5      .1       0
Bank Sta=202.5,222.5
XS Rating Curve= 0 ,0
Exp/Cntr=0.3,0.1

Type RM Length L Ch R = 1 ,2901.7  ,140.2,126.1,112
XS GIS Cut Line= 4
     1716015.263      238240.593      1715886.68      238121.277
     1715854.245      238030.922     1715759.255      237916.239
#Sta/Elev= 30
     9.7  964.04    19.5  963.23    29.2  961.35    68.2   948.7      78  944.34
    97.5  933.23   107.2  926.49   136.4     905   146.2  897.25   155.9  888.39
   165.7  882.17   175.4  877.85   194.6  876.65   204.2  877.12  216.87  873.76
   223.4   871.9     233  872.35   236.3  873.58   242.6  876.22   261.8  887.51
   271.4  893.42   281.3  900.28   291.3  903.47   301.2  910.74   311.1   916.7
   321.1  924.92     331  935.26   340.9   947.3   390.5  988.95   420.3 1012.58
#Mann= 3 , 0 , 0
     9.7      .1       0  216.87    .045       0   236.3      .1       0
Bank Sta=216.87,236.3
XS Rating Curve= 0 ,0
Exp/Cntr=0.3,0.1

Type RM Length L Ch R = 1 ,2775.6  ,288.1,289.5,290.9
XS GIS Cut Line= 4
     1716129.689      238149.828     1716051.439       238066.43
     1715940.242      237978.914     1715807.424       237886.25
#Sta/Elev= 30
     9.5  963.41    19.1  962.24    28.6  959.92    38.1  957.02   104.8  935.51
   114.4  931.24   134.6  907.39   154.8     884   164.9  874.81     175  871.79
   195.2   871.5   205.4  869.71   215.4  867.05   225.4  869.56   245.8  880.11
     266  889.23   276.1  894.28   286.2  899.95   296.4  906.42   306.5  913.19
   316.6  920.28   326.7  930.43   336.8  938.18   357.1  953.12   367.2  960.94
   377.3  968.09   387.4   972.2   397.6  978.34   407.7  986.66   417.8  996.29
#Mann= 3 , 0 , 0
       0      .1       0   205.4    .045       0   225.4      .1       0
Bank Sta=205.4,225.4
XS Rating Curve= 0 ,0
Exp/Cntr=0.3,0.1

Type RM Length L Ch R = 1 ,2486.2  ,232.9,233.2,233.5
XS GIS Cut Line= 4
     1716338.698      237929.493     1716217.205        237835.8
     1716102.919      237734.899     1715874.348      237670.034
#Sta/Elev= 30
     9.6  960.11    19.2  955.42    57.5   942.7    67.1  938.96    86.3  928.89
    95.9  921.82   105.5  912.58   143.8  891.86     163  884.21   201.1  865.08
   210.6  862.62   220.1  862.67   234.1  859.96   239.2  858.65   248.7  858.38
  252.45  859.92   258.2   862.3   267.8  870.22   277.3  878.82   305.9  900.79
   315.8  913.92   335.6  927.88   365.3  946.29   385.1  960.02     395  970.72
   404.9  979.96   434.6  999.78   464.3 1018.83   474.2 1029.83   543.5 1071.01
#Mann= 3 , 0 , 0
     9.6      .1       0   234.1    .045       0  252.45      .1       0
Bank Sta=234.1,252.45
XS Rating Curve= 0 ,0
Exp/Cntr=0.3,0.1

Type RM Length L Ch R = 1 ,2253    ,237.5,239.8,242.2
XS GIS Cut Line= 4
     1716485.931      237781.231     1716336.639      237631.939
     1716252.211      237555.748     1716110.126      237438.374
#Sta/Elev= 30
    10.1  991.48    20.1  981.17    30.2  972.47    50.3  962.68    80.4  940.29
    90.5  933.31   120.6  915.62   130.7  908.11   140.8  899.48   160.9  885.71
     181  871.01     191  864.69   201.1  862.32   211.1  858.59   220.6  857.46
   230.1  857.09  235.17  855.86     249  853.26  254.78  855.15   258.5  856.74
   344.3  907.37     354  914.89   363.7  919.63   373.4  922.23   402.5  936.91
   431.6  953.24     451  962.73   460.7  968.46   470.4  973.26   509.1  988.72
#Mann= 3 , 0 , 0
    10.1     .08       0  235.17    .045       0  254.78      .1       0
Bank Sta=235.17,254.78
XS Rating Curve= 0 ,0
Exp/Cntr=0.3,0.1

Type RM Length L Ch R = 1 ,2013.1  ,202.6,197.3,191.9
XS GIS Cut Line= 4
     1716680.525      237610.317     1716517.848       237499.12
     1716397.385      237368.361     1716208.968      237270.549
#Sta/Elev= 30
     9.9 1019.92      69  981.69    78.8  972.79    88.7  966.68    98.5   962.3
   147.8  929.04   167.5  915.54   187.2  898.44   256.3   858.3   285.9  848.26
   305.7  847.39   325.5  845.88  328.68  847.19   335.3  850.29     365  878.16
   374.8  886.37   395.1  900.87   405.2  911.22   415.3  919.65   425.4  926.38
   445.6  936.61   455.7  945.01   475.9  953.58     486  959.71   496.1   968.3
   516.4  981.39   536.6  992.21   566.9 1005.96     577 1011.74   587.1 1021.51
#Mann= 3 , 0 , 0
     9.9     .08       0   305.7    .045       0  328.68      .1       0
Bank Sta=305.7,328.68
XS Rating Curve= 0 ,0
Exp/Cntr=0.3,0.1

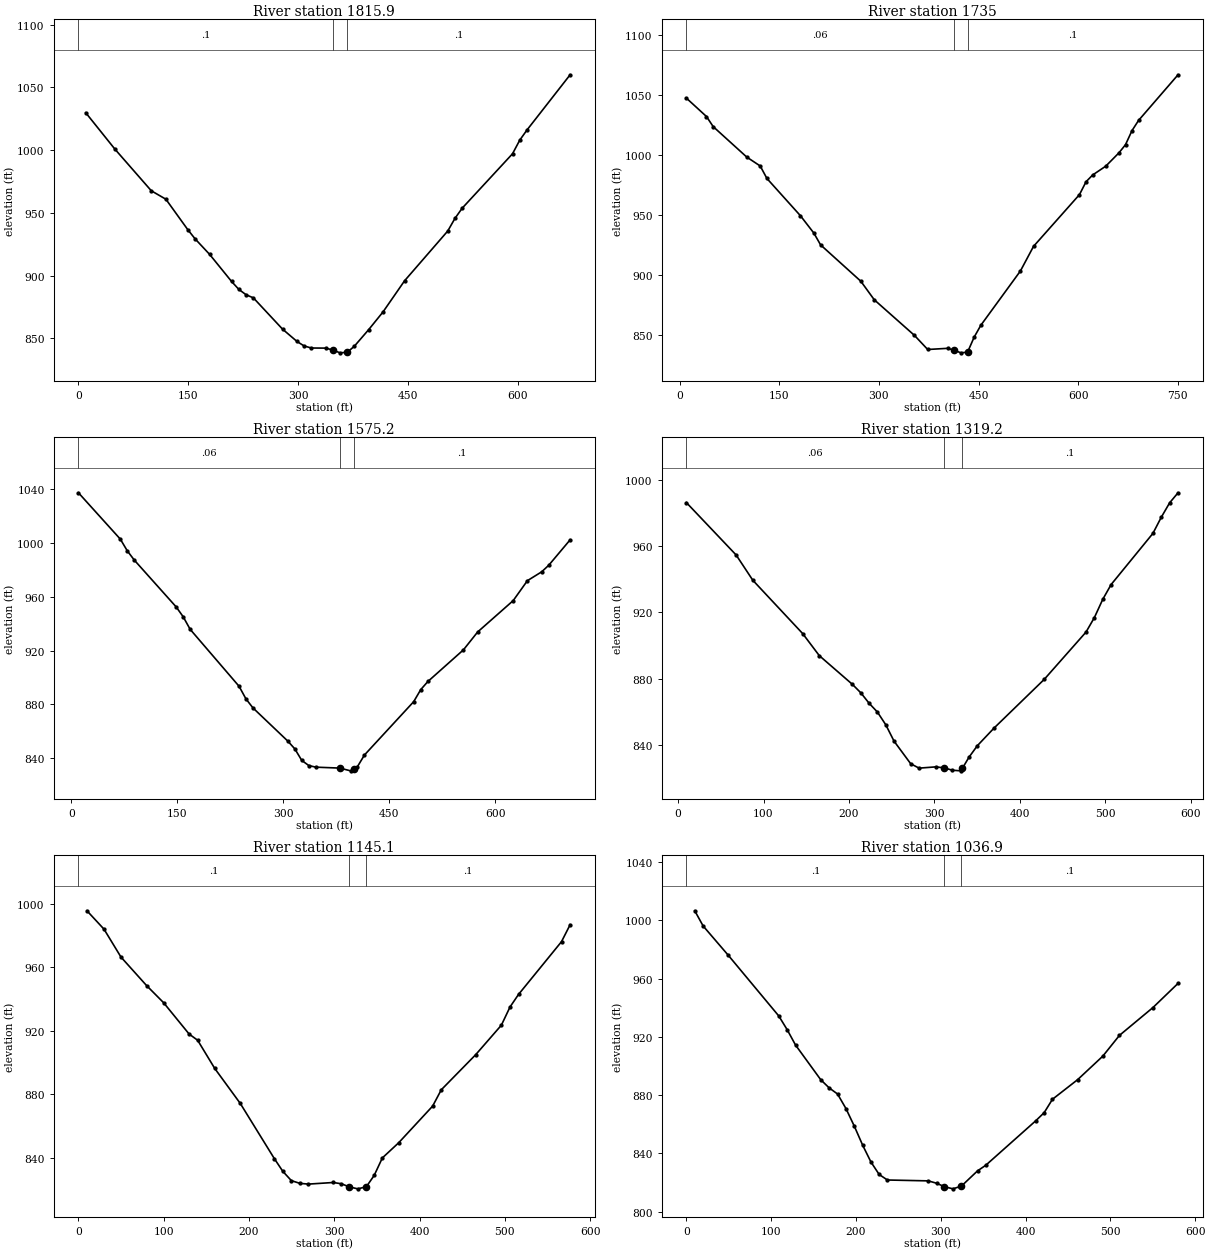
Type RM Length L Ch R = 1 ,1815.9  ,88.8,80.9,73
XS GIS Cut Line= 4
     1716735.792      237572.193     1716626.902      237304.601
     1716522.645      237231.621     1716285.172      237136.632
#Sta/Elev= 30
      10 1029.84    49.8 1000.86    99.6  967.63   119.5  960.92   149.4  936.68
   159.4  929.35   179.3  916.93   209.2  895.42   219.2  889.05   229.1  884.79
   239.1  882.28   278.9  857.39   298.7  847.54   308.5  843.94   318.3  842.34
   337.8  842.26   347.4  840.79   357.4  838.49   367.4  838.95     377  843.74
   396.6  856.97   416.2  871.08   445.7  895.94   504.7   935.6   514.5  945.63
   524.4  953.78   593.2  997.16   603.1 1008.03   612.9 1016.06   671.9  1060.1
#Mann= 3 , 0 , 0
       0      .1       0   347.4    .045       0   367.4      .1       0
Bank Sta=347.4,367.4
XS Rating Curve= 0 ,0
Exp/Cntr=0.3,0.1

Type RM Length L Ch R = 1 ,1735    ,157.7,159.8,161.9
XS GIS Cut Line= 4
     1717012.057      237287.022     1716686.703      237213.921
     1716552.855      237172.737      1716282.07      237115.079
#Sta/Elev= 30
    10.1  1047.2    40.4 1031.89    50.5 1023.49   101.1  998.16   121.3  990.77
   131.4  980.41   181.9   949.4   202.1  934.98   212.2   925.2   272.8  894.97
     293  879.58   353.5  849.98   373.5  838.24   403.5  839.21   413.5  837.56
   423.5  835.46   433.5  836.03   443.5  848.59   453.5  858.39   513.1  903.53
   532.8  923.95     602     967   611.9  977.68   621.8  983.28   641.6  990.64
   661.4 1001.69   671.3 1008.49   681.1  1020.2     691 1028.68   750.4 1066.59
#Mann= 3 , 0 , 0
    10.1     .06       0   413.5    .045       0   433.5      .1       0
#XS Ineff= 2 , 0
       0     403                       0
Permanent Ineff=
       F       F
Bank Sta=413.5,433.5
XS Rating Curve= 0 ,0
Exp/Cntr=0.3,0.1

Type RM Length L Ch R = 1 ,1575.2  ,252.8,256,259.1
XS GIS Cut Line= 4
     1717032.648      237160.381     1716757.745      237079.043
     1716602.275      237016.238     1716351.053      237031.682
#Sta/Elev= 30
     9.9 1037.54    69.2    1003    79.1  994.26      89  987.37   148.3  952.48
   158.2  945.15   168.1  935.78   237.3  893.37   247.1  883.94     257  877.23
   306.4  852.47   316.3  846.69   326.1  838.11     336   834.3   345.9  833.07
  380.05  832.38   395.2  830.33  400.01  831.87     405   833.5   414.9  842.13
   484.6  881.88   494.6  890.86   504.7  896.91     555  920.48   575.2  933.83
   625.5  957.19   645.6  972.04   665.8  978.63   675.9  983.57   706.1 1002.48
#Mann= 3 , 0 , 0
     9.9     .06       0  380.05    .045       0  400.01      .1       0
Bank Sta=380.05,400.01
XS Rating Curve= 0 ,0
Exp/Cntr=0.3,0.1

Type RM Length L Ch R = 1 ,1319.2  ,178.4,174.1,169.7
XS GIS Cut Line= 4
     1717082.069      236955.491     1716867.933      236862.887
     1716748.689      236796.423     1716601.246      236639.404
#Sta/Elev= 30
     9.7  986.29      68  954.63    87.5   939.4   145.8  907.26   165.3  893.92
   204.1  876.57   213.9  871.49   223.6  865.19   233.3   859.9   243.1  852.22
   252.8  842.32   272.3  828.68   282.1  826.04   301.6   826.8   311.3  826.22
   321.1  824.78   330.8  824.41  332.74   825.9   340.6   832.7   350.3  839.58
   369.8   850.2   428.6  879.61   477.5  908.15   487.3  916.91   497.1  927.91
   506.9  936.84   555.8  967.69   565.6  977.45   575.4  986.16   585.2  992.19
#Mann= 3 , 0 , 0
     9.7     .06       0   311.3    .045       0  332.74      .1       0
Bank Sta=311.3,332.74
XS Rating Curve= 0 ,0
Exp/Cntr=0.3,0.1

Type RM Length L Ch R = 1 ,1145.1  ,98.6,108.2,117.8
XS GIS Cut Line= 4
     1717110.474      236862.634     1716903.119      236674.972
     1716803.497      236640.219     1716613.518      236617.051
#Sta/Elev= 30
      10  995.51      30  983.92    49.9  966.37    79.9  948.46    99.9  937.65
   129.8  917.94   139.8  914.04   159.8  896.33   189.8  874.27   229.7  839.58
   239.7  831.54   249.7   825.7   259.7  823.99   269.7  823.52   298.8  824.53
   308.4  823.73   317.6  821.77   327.6  820.54   337.6  821.84   346.8  828.97
   356.4  839.99   375.6  849.56   415.4  872.62   425.5  882.86   465.8  904.92
     496  923.53   506.1  934.96   516.1  942.88   566.5  976.08   576.6  986.75
#Mann= 3 , 0 , 0
       0      .1       0   317.6    .045       0   337.6      .1       0
Bank Sta=317.6,337.6
XS Rating Curve= 0 ,0
Exp/Cntr=0.3,0.1

Type RM Length L Ch R = 1 ,1036.9  ,139.9,136.3,132.7
XS GIS Cut Line= 4
     1717162.378      236780.459     1717004.849      236644.552
     1716888.504      236542.621     1716683.614      236470.549
#Sta/Elev= 30
     9.9 1006.66    19.8  996.21    49.5  976.05     109  934.41   118.9  924.98
   128.8  914.41   158.5  890.61   168.4  885.01   178.3  880.81   188.2  870.84
   198.1  858.69   208.1  845.43   217.7   834.1   227.4  825.53   237.1  821.73
   285.4  821.13   295.1  819.51   304.4  817.13   314.4  815.66   324.4  817.54
   343.4     828   353.1  831.84   412.1  862.42     422  867.99   431.8  877.19
   461.5  890.67   491.1  906.76   510.8  921.07   550.3  940.18   579.9  956.79
#Mann= 3 , 0 , 0
       0      .1       0   304.4    .045       0   324.4      .1       0
Bank Sta=304.4,324.4
XS Rating Curve= 0 ,0
Exp/Cntr=0.3,0.1

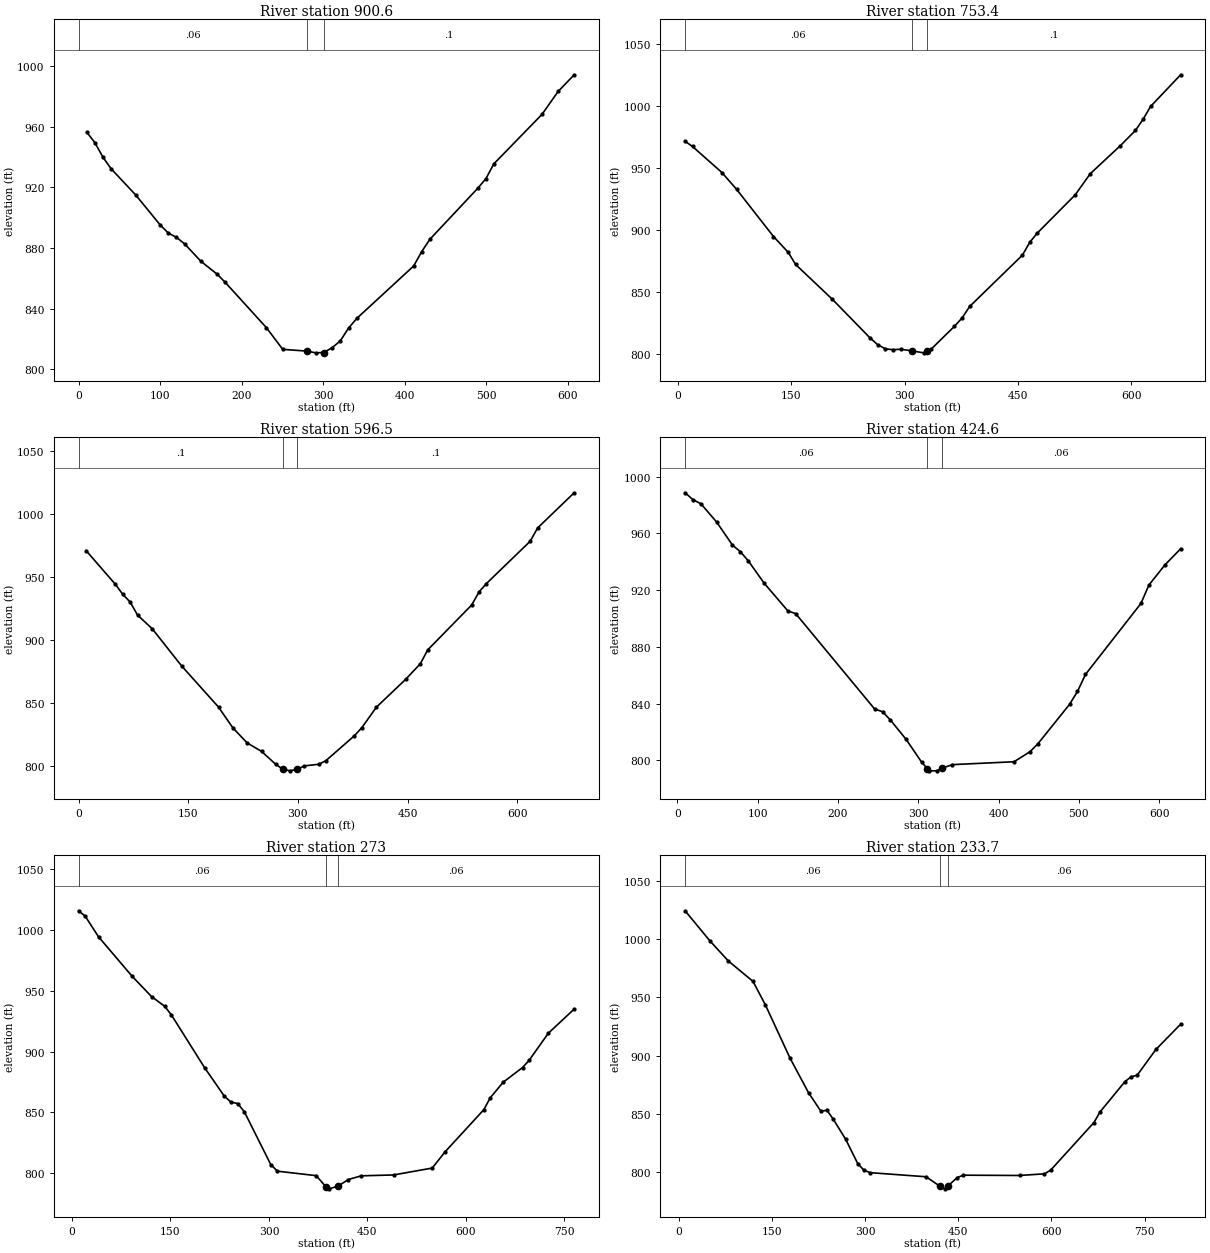
Type RM Length L Ch R = 1 ,900.6   ,144.7,147.2,149.8
XS GIS Cut Line= 4
     1717232.391      236657.422     1717088.247      236518.769
     1716935.866      236419.927     1716717.591      236359.524
#Sta/Elev= 30
      10  956.33      20  949.32      30  939.69      40  932.11      70  914.94
     100  895.23     110  889.82     120  887.01     130  882.71     150  871.25
     170   862.7     180  857.27   230.3  827.55   250.5  813.17   280.8  812.01
   290.8  810.88   300.8   811.1     311  814.22   321.1  818.73   331.2  827.18
   341.3  833.54   411.2  868.16     421  877.59   430.9  885.63     490  919.45
   499.8   925.7   509.6  935.47   568.7  968.09   588.4  983.13   608.1  994.13
#Mann= 3 , 0 , 0
       0     .06       0   280.8    .045       0   300.8      .1       0
Bank Sta=280.8,300.8
XS Rating Curve= 0 ,0
Exp/Cntr=0.3,0.1

Type RM Length L Ch R = 1 ,753.4   ,156.7,156.9,156.8
XS GIS Cut Line= 4
     1717281.812      236594.273     1717162.378      236404.826
     1717036.081      236303.239     1716760.148      236262.055
#Sta/Elev= 30
     9.7   971.7    19.5  967.53    58.4  946.55    77.9  932.93   126.6  895.01
   146.1  882.28   155.8  872.52   204.5  844.41   254.3  813.31   264.5  807.77
   274.6  804.59   284.7  803.81   294.9  804.23  309.11  802.94   325.3  801.31
  329.75  802.59   335.4  804.49   365.8  822.62   375.9  829.32     386  838.65
   455.8  880.03   465.7  890.54   475.7  897.96   525.5   928.5   545.5  945.62
   585.3  968.21   605.2  980.46   615.2  989.32   625.2  999.75     665  1025.3
#Mann= 3 , 0 , 0
     9.7     .06       0  309.11    .045       0  329.75      .1       0
Bank Sta=309.11,329.75
XS Rating Curve= 0 ,0
Exp/Cntr=0.3,0.1

Type RM Length L Ch R = 1 ,596.5   ,167.8,171.9,176.4
XS GIS Cut Line= 4
     1717395.754      236451.502     1717263.965      236299.121
     1717134.922      236194.788     1716824.669      236179.687
#Sta/Elev= 30
    10.1  970.97    50.4  944.03    60.4  936.18    70.5  930.06    80.6   919.7
   100.7  908.84     141  879.26   191.4  846.65   211.2  830.03   230.7  818.14
   250.3   811.5   269.8  801.12   279.3  797.42   289.3  796.04   299.3  797.32
   308.8  799.97   328.4  801.24   338.1  804.02   377.4  823.94   387.4  830.26
   407.5  846.64   447.6  868.77   467.6  881.14   477.6  892.06   537.7  927.67
   547.8  938.04   557.8  944.65   617.9  978.36   627.9  988.83     678  1016.8
#Mann= 3 , 0 , 0
       0      .1       0   279.3    .045       0   299.3      .1       0
Bank Sta=279.3,299.3
XS Rating Curve= 0 ,0
Exp/Cntr=0.3,0.1

Type RM Length L Ch R = 1 ,424.6   ,161.3,151.5,141.8
XS GIS Cut Line= 4
     1717450.666      236415.809     1717347.706      236160.468
     1717252.983      236052.017     1717048.436      236017.697
#Sta/Elev= 30
     9.8  988.59    19.7  983.69    29.5  980.83    49.2  967.86    68.8  951.69
    78.7  947.01    88.5  940.58   108.2  924.87   137.7  905.35   147.5  903.38
   245.8  836.13   255.7  834.23   265.5  828.32   284.9   814.8   304.1   798.8
   311.2  794.21   313.7  792.57   323.3  792.57  329.27  794.34   342.5  796.95
   419.3  798.98   439.1  806.01   448.9  811.57   488.4  839.44   498.3  848.53
   508.2  860.51   577.3  910.59   587.2  923.54     607  937.65   626.7  949.11
#Mann= 3 , 0 , 0
     9.8     .06       0   311.2    .045       0  329.27     .06       0
Bank Sta=311.2,329.27
XS Rating Curve= 0 ,0
Exp/Cntr=0.3,0.1

Type RM Length L Ch R = 1 ,273     ,39.7,39.3,38.9
XS GIS Cut Line= 4
     1717578.337      236315.594     1717453.412      236028.679
     1717243.373      235921.601     1717037.453      235987.495
#Sta/Elev= 30
    10.1  1015.6    20.2 1011.11    40.4  994.24    90.9  962.22   121.1  945.18
   141.3  937.11   151.4  930.07   201.9   886.8   232.2  863.24   242.3  858.49
   252.4  857.29   262.5  850.57   302.8  807.15   312.9  801.76   371.9   798.1
  386.52  789.14   391.5  787.26  405.02  789.45     421  794.92   440.6  797.95
   489.8  798.66   548.7  804.33   568.3  817.67   627.3  852.28   637.1  862.03
   656.8  874.85   686.3   886.9   696.1  892.67   725.6  915.08   764.9  934.87
#Mann= 3 , 0 , 0
    10.1     .06       0  386.52    .045       0  405.02     .06       0
Bank Sta=386.52,405.02
XS Rating Curve= 0 ,0
Exp/Cntr=0.3,0.1

Type RM Length L Ch R = 1 ,233.7   ,118.6,116.7,114.8
XS GIS Cut Line= 4
     1717611.284      236301.866     1717461.992      235987.667
     1717272.545      235895.003     1717036.767      235976.341
#Sta/Elev= 30
     9.9 1024.49    49.7  998.73    79.5  981.35   119.3  963.79   139.1  943.73
   178.9  897.87   208.7  868.11   228.6  852.23   238.5  852.92   248.5  845.39
   268.4  828.23   288.2  806.98   298.2  801.43   308.1  799.36   398.1  795.83
   420.1  787.79   428.2  785.45  433.32  787.88   448.3  795.18   458.3  797.19
   548.7  796.93   588.7  798.35   598.7  801.47   668.5  842.43   678.5  851.66
   718.4  877.57   728.4   881.8   738.3  883.19   768.3  905.24   808.2  926.98
#Mann= 3 , 0 , 0
     9.9     .06       0   420.1    .045       0  433.32     .06       0
Bank Sta=420.1,433.32
XS Rating Curve= 0 ,0
Exp/Cntr=0.3,0.1

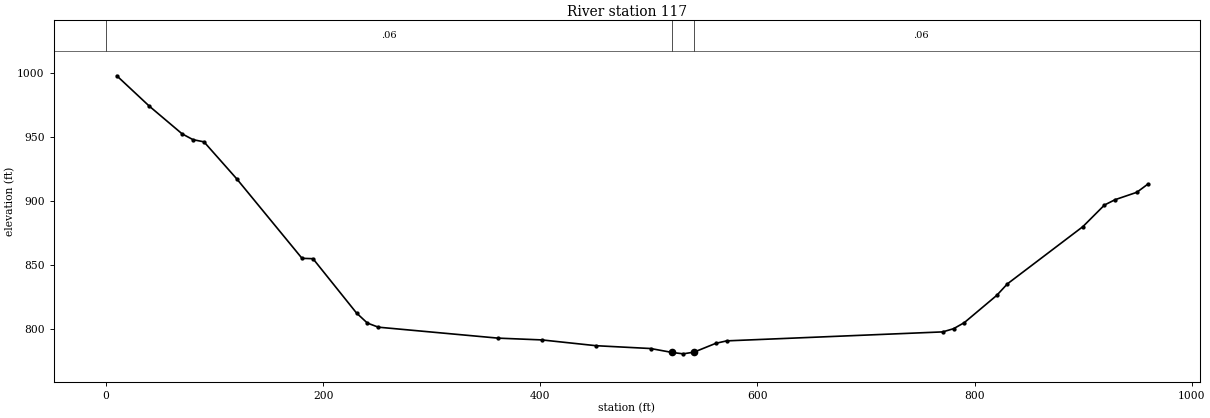
Type RM Length L Ch R = 1 ,117     ,121.4,117,112.7
XS GIS Cut Line= 4
     1717642.172      236283.162     1717552.597      235891.914
     1717366.239      235817.783     1717037.796      235958.838
#Sta/Elev= 30
      10  997.94    40.1  974.11    70.2  952.56    80.3  948.02    90.3  946.34
   120.4  917.52   180.6  855.37   190.7  855.09   230.8  812.67   240.8  804.81
   250.9   801.6   361.2  793.04   401.4  791.66   451.5  787.13   501.7  784.93
   521.7  781.83   531.7  780.78   541.7  782.13   561.8  789.02   571.8  790.91
   770.7  797.92   780.7  800.41   790.6  805.15   820.4  826.38   830.3  835.44
   899.8  880.12   919.7  897.01   929.6  901.21   949.5  906.94   959.4  913.17
#Mann= 3 , 0 , 0
       0     .06       0   521.7    .045       0   541.7     .06       0
Bank Sta=521.7,541.7
XS Rating Curve= 0 ,0
Exp/Cntr=0.3,0.1

Chan Stop Cuts=-1
Use User Specified Reach Order=0